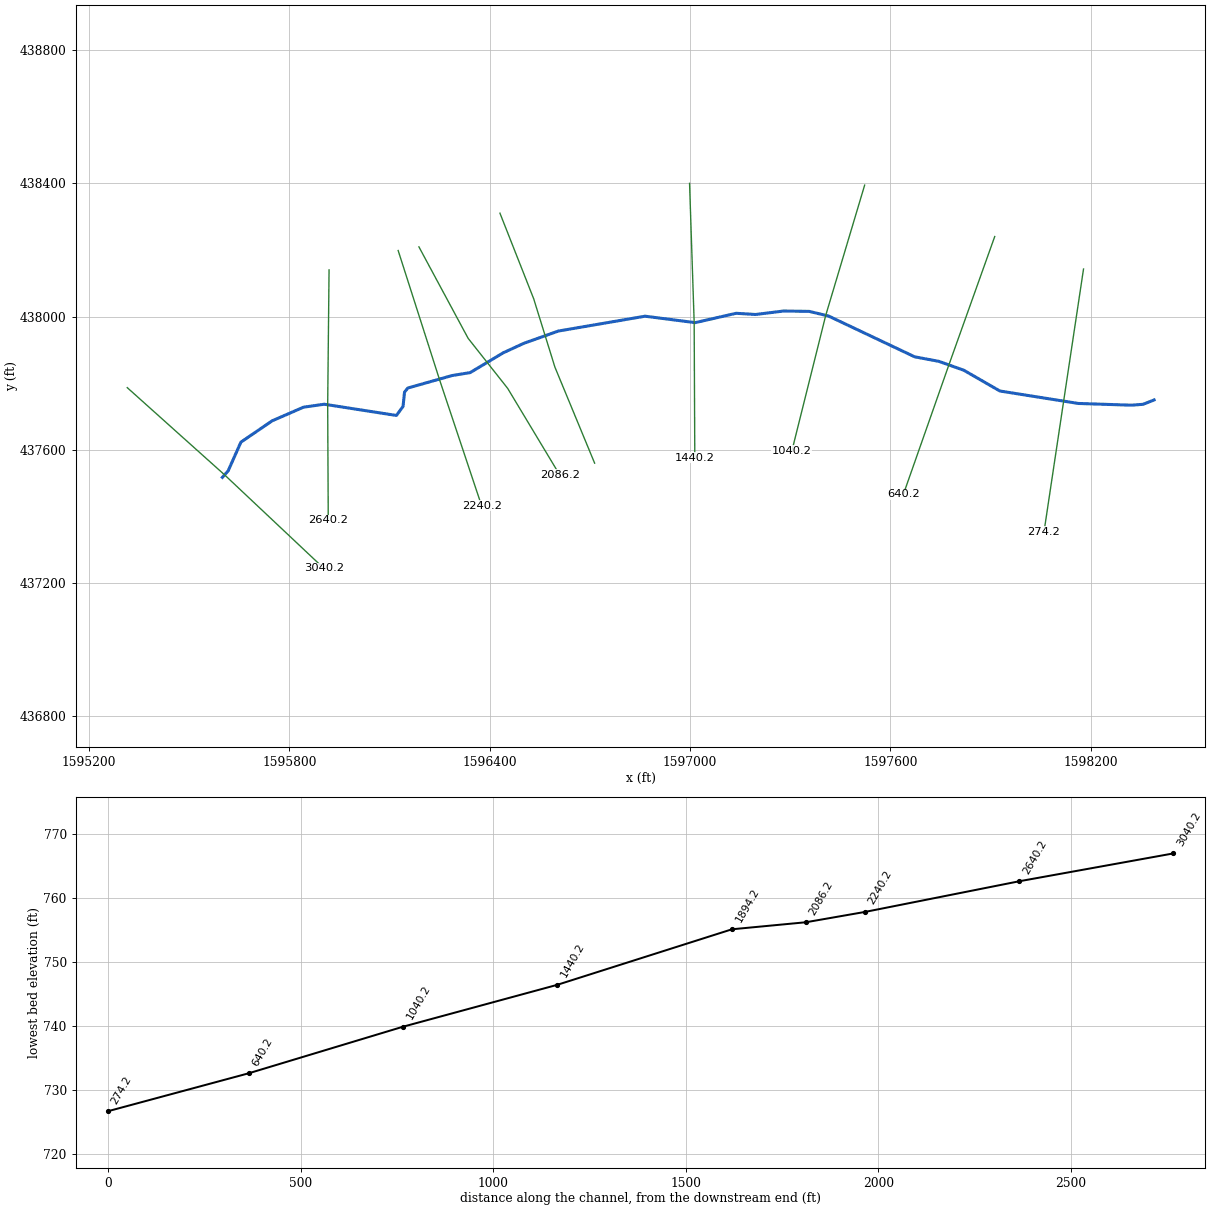
--- TRKCMPBR.prj (project) ---

Proj Title=TRKCMPBR
Current Plan=p01
Default Exp/Contr=0,0
English Units
Geom File=g01
Flow File=f01
Plan File=p01
BEGIN DESCRIPTION:
END DESCRIPTION:
DSS Export Rating Curves= 0
DSS Export Rating Curve Sorted= 0
DSS Export Volume Flow Curves= 0
DXF OffsetX= 0
DXF OffsetY= 0
DXF ScaleX= 0
DXF ScaleY= 0

--- TRKCMPBR.p01 (plan) ---

Plan Title=Floodplain
Program Version=4.00
Geom File=g01
Flow File=f01
K Sum by GR=0
Std Step Tol=0.01
Critical Tol=0.01
Num of Std Step Trials=20
Max Error Tol=0.3
Flow Tol Ratio=0.001
Split Flow NTrial=30
Split Flow Tol=0.02
Split Flow Ratio=0.02
Log Output Level=0
Friction Slope Method=1
Unsteady Friction Slope Method=2
Unsteady Bridges Friction Slope Method=1
Global Log Level=0
CheckData=False
Run HTab=0
Run UNet=0
Run PostProcess=0
UNET Theta=0
UNET Theta Warmup=0
UNET ZTol=0
UNET ZSATol=0
UNET MxIter=0
UNET MaxInSteps=0
UNET DtIC=0
UNET DtMin=0
UNET MaxCRTS=0
UNET WFStab=0
UNET SFStab=0
UNET WFX=0
UNET SFX=0
UNET DSS MLevel=0
UNET DZMax Abort=0
UNET Convert EG Bridges=0
UNET Use Existing IB Tables=0
UNET Froude Limit=0
UNET Froude Power=0
Write IC File=0
Echo Input=False
Echo Output=False
Write Detailed=0

--- TRKCMPBR.f01 (steady flow) ---

Flow Title=NFF Regression Equation
Program Version=4.00
Number of Profiles=1
Profile Names=P100yr
River Rch & RM=TRKCMPBR,Main      ,3040.2
     392
River Rch & RM=TRKCMPBR,Main      ,2086.2
     410
River Rch & RM=TRKCMPBR,Main      ,274.2
     452
Boundary for River Rch & Prof#=TRKCMPBR,Main      ,1
Up Type=0
Dn Type=3
Dn Slope=0.016924

--- TRKCMPBR.g01 (geometry) ---

Geom Title=USGS 10m DEM
Program Version=4.00

River Reach=TRKCMPBR        ,Main
Reach XY= 30
     1595598.968      437517.181     1595616.249      437536.659
     1595654.507      437622.876     1595747.957      437686.832
     1595841.854      437727.765     1595904.084      437736.723
     1596120.327       437702.99     1596140.218      437730.063
     1596144.622      437772.798     1596154.336      437785.299
     1596287.115      437822.821     1596341.296      437831.649
     1596439.978      437890.893     1596501.806      437919.456
     1596605.233      437956.351     1596865.063      438000.954
     1597015.403      437981.641     1597138.315      438009.719
     1597195.984      438006.107      1597280.54      438016.528
     1597357.226      438015.398     1597414.943      438001.407
     1597672.927      437879.008     1597745.249      437865.425
     1597819.942      437838.805     1597928.105      437776.433
     1598163.089      437739.037     1598322.011      437733.836
     1598356.834      437736.465     1598390.019      437749.557

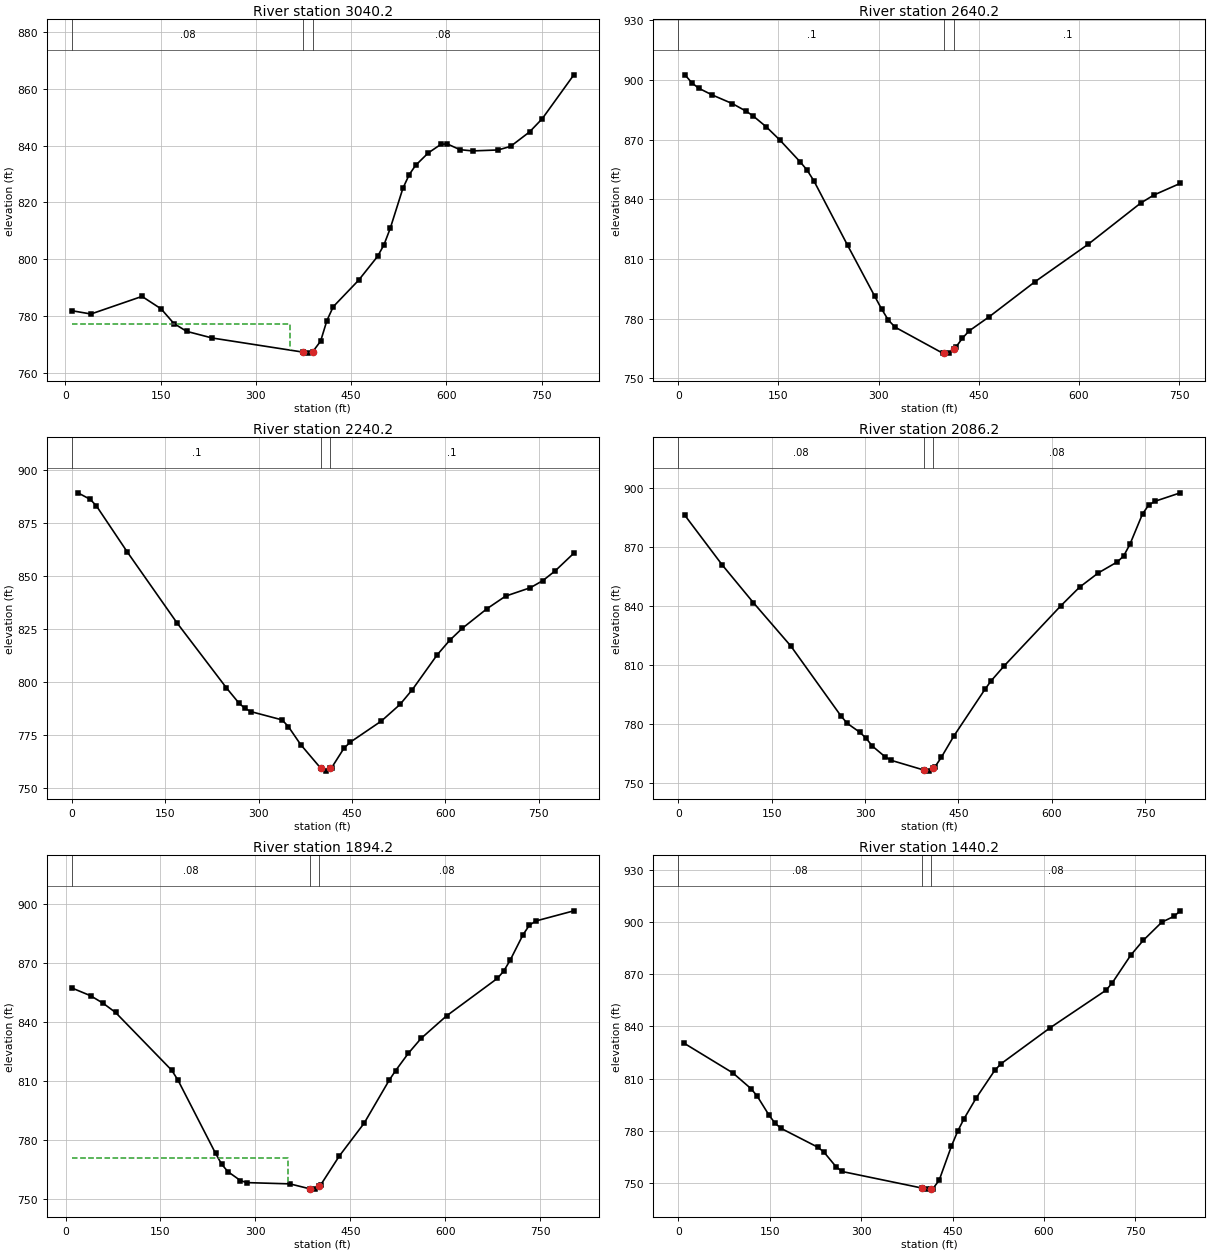
Type RM Length L Ch R = 1 ,3040.2  ,419.2,400,381.7
XS GIS Cut Line= 3
     1595314.035      437786.511     1595605.605      437524.662
     1595902.937      437244.067
#Sta/Elev= 30
      10  781.94    40.2  780.78   120.6  786.97   150.7  782.59   170.8  777.44
   190.9  774.68   231.1  772.34   374.3  767.37   381.8  767.02   389.3  767.47
   401.9  771.23   411.8  778.47   421.8  783.35   461.7  792.65   491.6  801.04
   501.6  805.09   511.5  810.87   531.5     825   541.5  829.82   551.4  833.04
   571.4  837.43   591.3  840.44   601.3  840.61   621.2  838.58   641.2  838.14
   681.1  838.47     701  839.72   730.9  844.81   750.9  849.46   800.7   864.9
#Mann= 3 , 0 , 0
      10     .08       0   374.3    .045       0   389.3     .08       0
#XS Ineff= 2 , 0
          354.25  777.27
Permanent Ineff=
       F       F
Bank Sta=374.3,389.3
XS Rating Curve= 0 ,0
Exp/Cntr=0.3,0.1

Type RM Length L Ch R = 1 ,2640.2  ,392.6,400,407.3
XS GIS Cut Line= 3
     1595918.565       438140.06     1595914.427      437734.293
     1595916.147      437388.474
#Sta/Elev= 30
    10.1  902.64    20.3  898.64    30.4  895.95    50.7  892.54    81.2  888.13
   101.4   884.4   111.6   882.1   131.9  876.45   152.2  869.82   182.6  858.83
   192.7   854.8   202.9  849.42   253.6  816.84   294.2  791.25   304.3  784.93
   314.5   779.3   324.6  775.74   395.6  762.71   398.3   762.7   405.8  762.67
   413.3  764.98   415.7  765.72   425.5  770.22   435.4  773.83   465.1  780.86
   534.2  798.61   613.3  817.33   692.3  838.14   712.1   842.2   751.6  848.06
#Mann= 3 , 0 , 0
       0      .1       0   398.3    .045       0   413.3      .1       0
Bank Sta=398.3,413.3
XS Rating Curve= 0 ,0
Exp/Cntr=0.3,0.1

Type RM Length L Ch R = 1 ,2240.2  ,145.9,154,161.9
XS GIS Cut Line= 3
     1596125.545      438198.149     1596249.609      437810.114
     1596375.586      437431.817
#Sta/Elev= 30
     9.9  889.24    29.8  886.13    39.7  883.01    89.4   861.2   168.9  827.87
   248.4  797.14   268.3  790.02   278.2  787.45   288.2  785.92   337.8  782.05
   347.8  778.87   367.6  770.38   399.9  759.19   407.4  757.88   414.9  759.16
   417.4  759.59   437.3  768.81   447.3  771.58   497.1  781.53     527  789.35
   546.9  796.38   586.8  812.82   606.7   819.6   626.7  825.22   666.6  834.53
   696.5  840.48   736.3  844.45   756.3   847.8   776.2  852.42   806.1  860.75
#Mann= 3 , 0 , 0
       0      .1       0   399.9    .045       0   414.9      .1       0
Bank Sta=399.9,414.9
XS Rating Curve= 0 ,0
Exp/Cntr=0.3,0.1

Type RM Length L Ch R = 1 ,2086.2  ,200.3,192,183.7
XS GIS Cut Line= 4
     1596187.765      438209.108     1596335.133        437934.6
     1596453.605      437784.343     1596609.641      437524.283
#Sta/Elev= 30
    10.1  886.23    70.4  860.94   120.6  841.74   180.9  819.67   261.3  784.25
   271.4  780.49   291.5  775.99   301.5  773.01   311.6  768.98   331.7  763.65
   341.8  761.75   394.7  756.78   402.2  756.26   409.7   757.9   412.3  758.46
   422.3  763.18   442.5  774.03   492.8   797.9   502.9  802.23   523.1  809.54
   614.1  840.05   644.4  849.56   674.8  856.86   705.1   862.4   715.2  865.39
   725.3  871.32   745.5  886.72   755.6  891.29   765.8  893.17   806.2  897.43
#Mann= 3 , 0 , 0
       0     .08       0   394.7    .045       0   409.7     .08       0
Bank Sta=394.7,409.7
XS Rating Curve= 0 ,0
Exp/Cntr=0.3,0.1

Type RM Length L Ch R = 1 ,1894.2  ,459.9,454,447.3
XS GIS Cut Line= 4
     1596430.488      438310.243     1596531.623      438053.072
     1596595.193      437847.914     1596714.112      437559.835
#Sta/Elev= 30
     9.9  857.32    39.5  853.38    59.2  849.59      79  844.88   167.8   815.5
   177.6  810.52   236.9  773.37   246.7  767.76   256.6     764   276.3  759.51
   286.1  758.47   354.4  757.83     386   755.3   393.5  755.16     401   756.9
   403.3  757.43   432.5  772.02   471.6  788.63   511.2  810.48   521.3  815.34
   541.4  824.12   561.5  831.68   601.7  843.12   682.1  862.19   692.2  865.94
   702.2  871.39   722.4  884.26   732.4   889.1   742.5   891.3   802.8  896.48
#Mann= 3 , 0 , 0
     9.9     .08       0     386    .045       0     401     .08       0
#XS Ineff= 2 , 0
          350.84  770.98
Permanent Ineff=
       F       F
Bank Sta=386,401
XS Rating Curve= 0 ,0
Exp/Cntr=0.3,0.1

Type RM Length L Ch R = 1 ,1440.2  ,407.3,400,394.4
XS GIS Cut Line= 3
     1596998.502      438399.714     1597012.307      437982.121
     1597014.179      437576.295
#Sta/Elev= 30
     9.9  830.22    89.5  813.24   119.4  804.17   129.3  800.02   149.2  788.81
   159.2  784.18   169.1   781.3   228.8  770.58   238.8  767.84   258.7  759.41
   268.6  756.61   400.4  747.05   407.9  746.47   415.4   746.7   417.8  746.78
     428  751.49   448.3  771.25   458.4  779.68   468.5  786.68   488.8   798.8
   519.3  814.71   529.4  818.44   610.6  839.26   701.9  860.74     712  864.92
   742.5  880.91   762.8  889.32   793.2  899.77   813.5  903.22   823.7  906.33
#Mann= 3 , 0 , 0
       0     .08       0   400.4    .045       0   415.4     .08       0
Bank Sta=400.4,415.4
XS Rating Curve= 0 ,0
Exp/Cntr=0.3,0.1

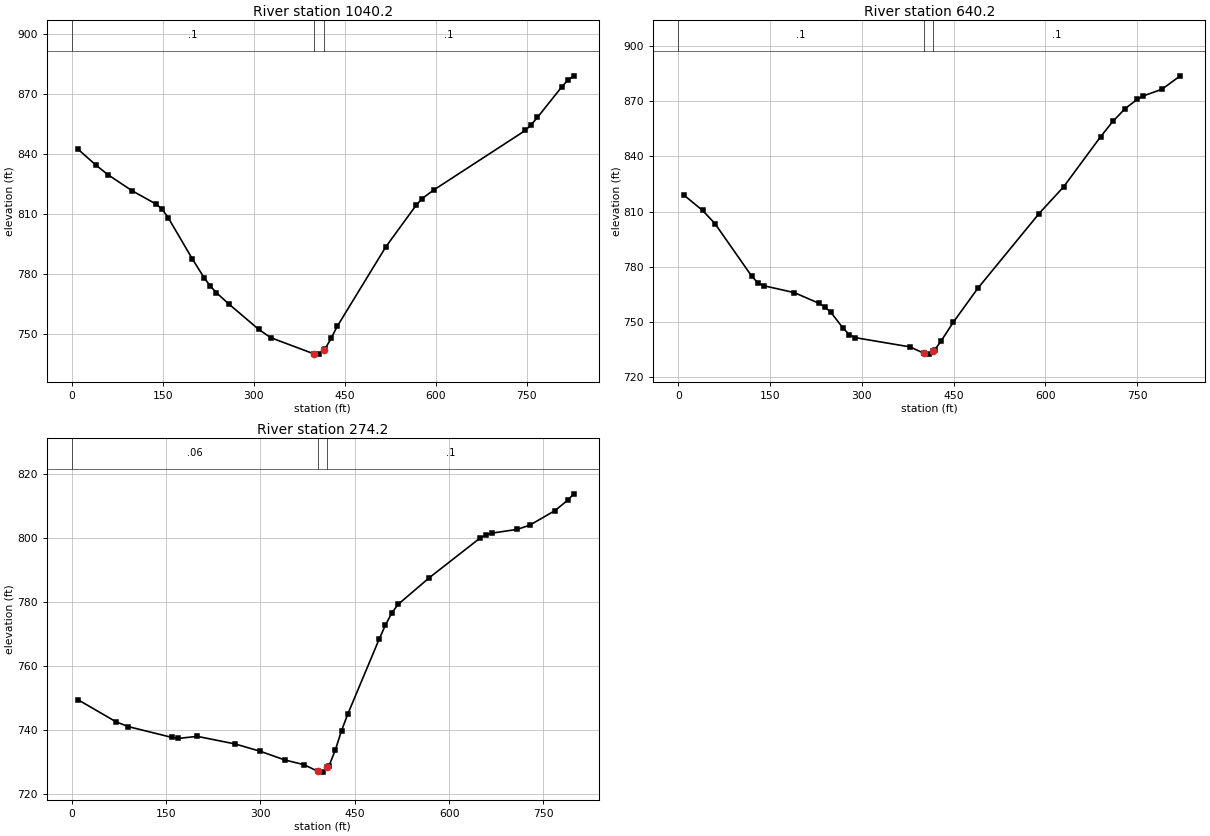
Type RM Length L Ch R = 1 ,1040.2  ,401.2,400,397.9
XS GIS Cut Line= 3
     1597523.033      438394.509     1597406.528      438003.916
     1597304.955      437596.094
#Sta/Elev= 30
     9.9  842.34    39.8   834.3    59.6  829.53    99.4  821.51   139.2  814.81
   149.1  812.28   159.1  807.99   198.8  787.47   218.7  777.85   228.7  773.82
   238.6  770.58   258.5  765.08   308.2   752.3   328.1  748.14   400.1  739.98
   407.6  739.93   415.1  741.85   417.6  742.49   427.6  747.78   437.6  753.73
   517.7  793.42   567.7  814.22   577.7  817.61   597.7  822.04   747.8  851.59
   757.8  854.53   767.8  858.09   807.9  873.33   817.9  876.69   827.9  878.88
#Mann= 3 , 0 , 0
       0      .1       0   400.1    .045       0   415.1      .1       0
Bank Sta=400.1,415.1
XS Rating Curve= 0 ,0
Exp/Cntr=0.3,0.1

Type RM Length L Ch R = 1 ,640.2   ,361.6,366,370.3
XS GIS Cut Line= 3
     1597912.677      438240.117     1597775.321      437854.708
     1597639.105      437466.449
#Sta/Elev= 30
      10  818.75    39.9  810.61    59.9  803.53   119.8  775.09   129.7  771.46
   139.7  769.78   189.6  766.05   229.5  760.32   239.5   758.3   249.5  755.33
   269.4  746.77   279.4  743.31   289.4  741.59   379.2  736.56   401.7  733.08
   409.2  732.66   416.7  734.37   419.2  734.95   429.2  739.55   449.3  749.83
   489.4  768.28   589.8  808.96   629.9  823.45   690.2  850.57   710.2  858.91
   730.3  865.83   750.4  870.96   760.4   872.8   790.5  876.37   820.6  883.67
#Mann= 3 , 0 , 0
       0      .1       0   401.7    .045       0   416.7      .1       0
Bank Sta=401.7,416.7
XS Rating Curve= 0 ,0
Exp/Cntr=0.3,0.1

Type RM Length L Ch R = 1 ,274.2   ,262.4,274.2,286.1
XS GIS Cut Line= 3
     1598178.671      438142.649      1598120.91      437757.932
     1598060.221      437353.146
#Sta/Elev= 30
      10  749.39    69.8  742.55    89.8  740.98   159.6  737.58   169.6  737.28
   199.5  737.92   259.4  735.56   299.3  733.28   339.2   730.5   369.1  729.07
   391.5  726.94     399  726.72   406.5  728.18     409  728.67     419  733.61
     429  739.76   438.9  744.92   488.9  768.46   498.8  772.81   508.8  776.58
   518.8  779.26   568.7  787.66   648.6  799.96   658.6  801.05   668.6  801.61
   708.5  802.78   728.5  804.12   768.4  808.67   788.4  811.89   798.3  813.91
#Mann= 3 , 0 , 0
       0     .06       0   391.5    .045       0   406.5      .1       0
Bank Sta=391.5,406.5
XS Rating Curve= 0 ,0
Exp/Cntr=0.3,0.1

Chan Stop Cuts=-1
Use User Specified Reach Order=0